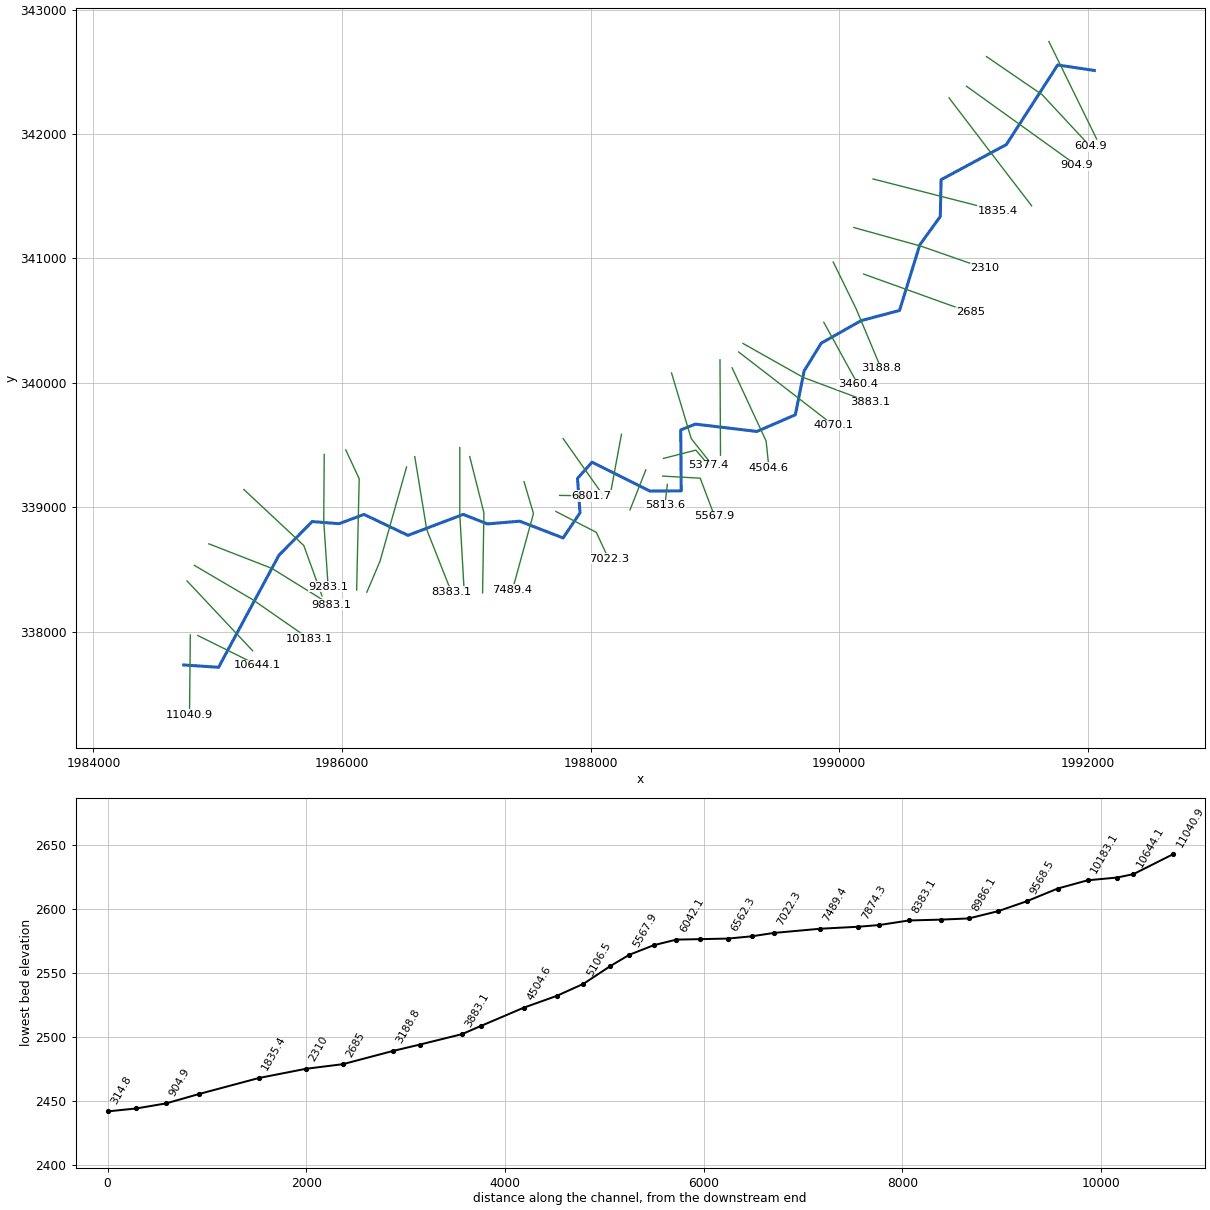
--- ShdsDthCrk.prj (project) ---

Proj Title=ShdsDthCrk
Current Plan=p01
Geom File=g01
Flow File=f01
Plan File=p01
DSS Export Rating Curves=0
DSS Export Rating Curve Sorted=0
DSS Export Volume Flow Curves=0
DXF OffsetX=0
DXF OffsetY=0
DXF ScaleX=0
DXF ScaleY=0

--- ShdsDthCrk.p01 (plan) ---

Plan Title=Floodplain
Program Version=4.00
Geom File=g01
Flow File=f01
K Sum by GR=0
Std Step Tol=0.01
Critical Tol=0.01
Num of Std Step Trials=20
Max Error Tol=0.3
Flow Tol Ratio=0.001
Split Flow NTrial=30
Split Flow Tol=0.02
Split Flow Ratio=0.02
Log Output Level=0
Friction Slope Method=1
Unsteady Friction Slope Method=2
Unsteady Bridges Friction Slope Method=1
Global Log Level=0
CheckData=False
Run HTab=0
Run UNet=0
Run PostProcess=0
UNET Theta=0
UNET Theta Warmup=0
UNET ZTol=0
UNET ZSATol=0
UNET MxIter=0
UNET MaxInSteps=0
UNET DtIC=0
UNET DtMin=0
UNET MaxCRTS=0
UNET WFStab=0
UNET SFStab=0
UNET WFX=0
UNET SFX=0
UNET DSS MLevel=0
UNET DZMax Abort=0
UNET Convert EG Bridges=0
UNET Use Existing IB Tables=0
UNET Froude Limit=0
UNET Froude Power=0
Write IC File=0
Echo Input=False
Echo Output=False
Write Detailed=0

--- ShdsDthCrk.f01 (steady flow) ---

Flow Title=NFF Regression Equation
Program Version=4.00
Number of Profiles=1
Profile Names=P100yr
River Rch & RM=ShdsDthCrk,Main      ,11040.9
582.6012
River Rch & RM=ShdsDthCrk,Main      ,9568.5
600.9599
River Rch & RM=ShdsDthCrk,Main      ,8986.1
668.9724
River Rch & RM=ShdsDthCrk,Main      ,7489.4
698.4661
River Rch & RM=ShdsDthCrk,Main      ,5567.9
767.8857
River Rch & RM=ShdsDthCrk,Main      ,2310
840.1132
River Rch & RM=ShdsDthCrk,Main      ,1238.1
2082.748
Boundary for River Rch & Prof#=ShdsDthCrk,Main      ,1
Up Type=0
Dn Type=3
Dn Slope=0.013974

--- ShdsDthCrk.g01 (geometry) ---

Geom Title=USGS 3m DEM
Program Version=4.00

River Reach=ShdsDthCrk     ,Main
Reach XY= 30
     1984726.518      337732.870     1985006.456      337714.268
     1985492.143      338614.814     1985759.592      338885.366
     1985976.518      338868.287     1986176.171      338942.939
     1986530.338      338774.537     1986974.782      338942.939
     1987169.227      338866.551     1987429.742      338888.286
     1987778.602      338753.703     1987914.479      338956.029
     1987894.256      339232.437     1988011.356      339362.420
     1988476.518      339130.440     1988728.854      339132.241
     1988724.782      339621.759     1988842.838      339668.634
     1989337.630      339609.606     1989646.657      339743.287
     1989717.838      340095.717     1989855.310      340318.962
     1990176.994      340500.616     1990485.199      340581.828
     1990648.393      341109.606     1990813.324      341337.037
     1990819.648      341632.825     1991344.574      341915.162
     1991757.796      342554.902     1992052.876      342510.630

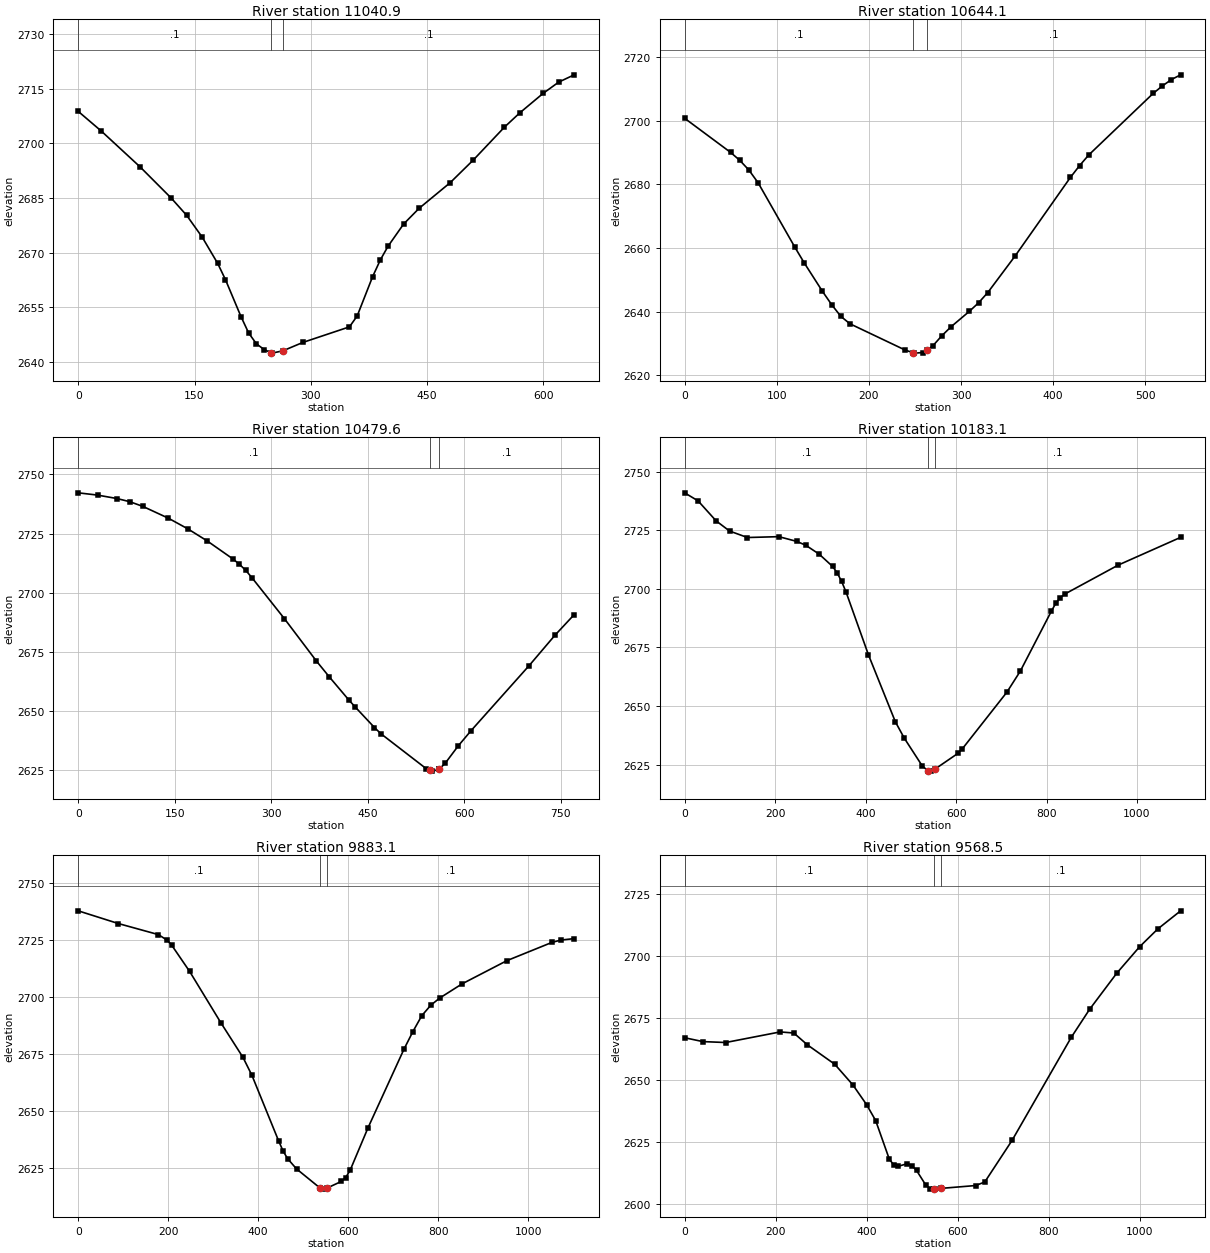
Type RM Length L Ch R = 1 ,11040.9,371.9,397,422
XS GIS Cut Line= 2
     1984779.076      337973.869     1984772.617      337334.335
#Sta/Elev= 30
       0 2708.80    30.0 2703.35    80.0 2693.52   119.9 2685.01   139.9 2680.25
   159.9 2674.28   179.9 2667.06   189.9 2662.61   209.9 2652.48   219.8 2647.97
   229.8 2645.00   239.8 2643.42   248.8 2642.54   249.8 2642.44   263.8 2643.06
   289.8 2645.38   349.8 2649.65   359.8 2652.65   379.7 2663.44   389.7 2668.05
   399.7 2671.82   419.7 2677.88   439.7 2682.20   479.7 2689.22   509.6 2695.46
   549.6 2704.45   569.6 2708.41   599.6 2713.74   619.6 2716.82   639.6 2718.83
#Mann= 3 , 0 , 0
       0     0.1       0   248.8   0.045       0   263.8     0.1       0
Bank Sta=   248.8,   263.8
Exp/Cntr=0.3,0.1

Type RM Length L Ch R = 1 ,10644.1,172.3,164.4,156.6
XS GIS Cut Line= 2
     1984839.369      337969.563     1985321.711      337730.545
#Sta/Elev= 30
       0 2700.70    49.8 2690.01    59.8 2687.51    69.8 2684.43    79.8 2680.42
   119.6 2660.24   129.6 2655.39   149.5 2646.40   159.5 2642.22   169.5 2638.53
   179.4 2636.20   239.2 2627.97   247.9 2627.12   249.2 2626.99   259.2 2627.18
   262.9 2627.94   269.2 2629.23   279.1 2632.44   289.1 2635.26   309.0 2640.11
   319.0 2642.79   329.0 2646.01   358.9 2657.58   418.7 2682.16   428.7 2685.88
   438.6 2689.20   508.4 2708.49   518.4 2710.85   528.4 2712.88   538.3 2714.35
#Mann= 3 , 0 , 0
       0     0.1       0   247.9   0.045       0   262.9     0.1       0
Bank Sta=   247.9,   262.9
Exp/Cntr=0.3,0.1

Type RM Length L Ch R = 1 ,10479.6,290,296.5,301.2
XS GIS Cut Line= 2
     1984752.926      338408.096     1985280.798      337846.824
#Sta/Elev= 30
       0 2742.23    30.0 2741.27    60.0 2739.82    80.0 2738.48   100.1 2736.52
   140.1 2731.48   170.1 2727.00   200.1 2721.91   240.2 2714.25   250.2 2712.03
   260.2 2709.42   270.2 2706.18   320.2 2688.98   370.2 2670.94   390.3 2664.20
   420.3 2654.53   430.3 2651.53   460.3 2642.80   470.3 2640.18   540.4 2625.45
   546.3 2624.80   550.4 2624.35   560.4 2625.08   561.3 2625.32   570.4 2627.77
   590.4 2635.04   610.4 2641.51   700.5 2669.03   740.5 2681.85   770.5 2690.63
#Mann= 3 , 0 , 0
       0     0.1       0   546.3   0.045       0   561.3     0.1       0
Bank Sta=   546.3,   561.3
Exp/Cntr=0.3,0.1

Type RM Length L Ch R = 1 ,10183.1,296.4,300,301.1
XS GIS Cut Line= 3
     1984811.926      338533.074     1985281.993      338257.166
     1985734.843      337942.678
#Sta/Elev= 30
       0 2740.99    29.7 2737.54    69.4 2729.04    99.1 2724.69   138.7 2721.91
   208.1 2722.28   247.8 2720.26   267.6 2718.62   297.3 2714.82   327.0 2709.56
   336.9 2706.90   346.8 2703.25   356.8 2698.61   406.3 2671.82   465.8 2643.23
   485.6 2636.23   525.2 2624.42   537.6 2622.36   545.1 2622.19   552.6 2622.96
   604.1 2629.77   614.0 2631.76   712.4 2655.91   742.0 2664.88   810.9 2690.56
   820.7 2693.93   830.6 2696.26   840.4 2697.78   958.6 2710.16  1096.4 2721.98
#Mann= 3 , 0 , 0
       0     0.1       0   537.6   0.045       0   552.6     0.1       0
Bank Sta=   537.6,   552.6
Exp/Cntr=0.3,0.1

Type RM Length L Ch R = 1 ,9883.1,323.3,314.7,310.3
XS GIS Cut Line= 3
     1984927.909      338706.668     1985435.354      338509.112
     1985909.547      338215.830
#Sta/Elev= 30
       0 2738.00    89.1 2732.42   178.2 2727.56   198.0 2725.05   207.9 2722.87
   247.5 2711.42   316.8 2688.92   366.3 2673.60   386.1 2665.74   445.5 2636.91
   455.4 2632.50   465.3 2629.18   485.1 2624.69     537 2616.35   544.5 2615.80
     552 2616.18   584.4 2619.15   594.3 2620.85   604.3 2624.10   644.1 2642.77
   723.8 2677.20   743.7 2684.97   763.6 2691.98   783.5 2696.55   803.4 2699.71
   853.2 2705.95   952.8 2716.14  1052.3 2724.10  1072.2 2725.15  1102.1 2725.80
#Mann= 3 , 0 , 0
       0     0.1       0     537   0.045       0     552     0.1       0
Bank Sta=     537,     552
Exp/Cntr=0.3,0.1

Type RM Length L Ch R = 1 ,9568.5,304,285.3,268.2
XS GIS Cut Line= 3
     1985209.849      339143.184     1985692.081      338693.076
     1985838.506      338288.253
#Sta/Elev= 30
       0 2666.85    40.0 2665.30    90.0 2664.93   209.9 2669.20   239.9 2668.76
   269.9 2663.97   329.8 2656.18   369.8 2647.82   399.8 2639.90   419.8 2633.46
   449.8 2617.90   459.8 2615.49   469.8 2615.03   489.7 2616.08   499.7 2615.26
   509.7 2613.33   529.7 2607.53   539.7 2605.89   547.4 2605.82   549.7 2605.80
   562.4 2606.08   639.7 2607.25   659.7 2608.68   719.7 2625.46   849.9 2667.05
   889.9 2678.26   950.0 2692.93  1000.0 2703.54  1040.1 2710.75  1090.2 2718.04
#Mann= 3 , 0 , 0
       0     0.1       0   547.4   0.045       0   562.4     0.1       0
Bank Sta=   547.4,   562.4
Exp/Cntr=0.3,0.1

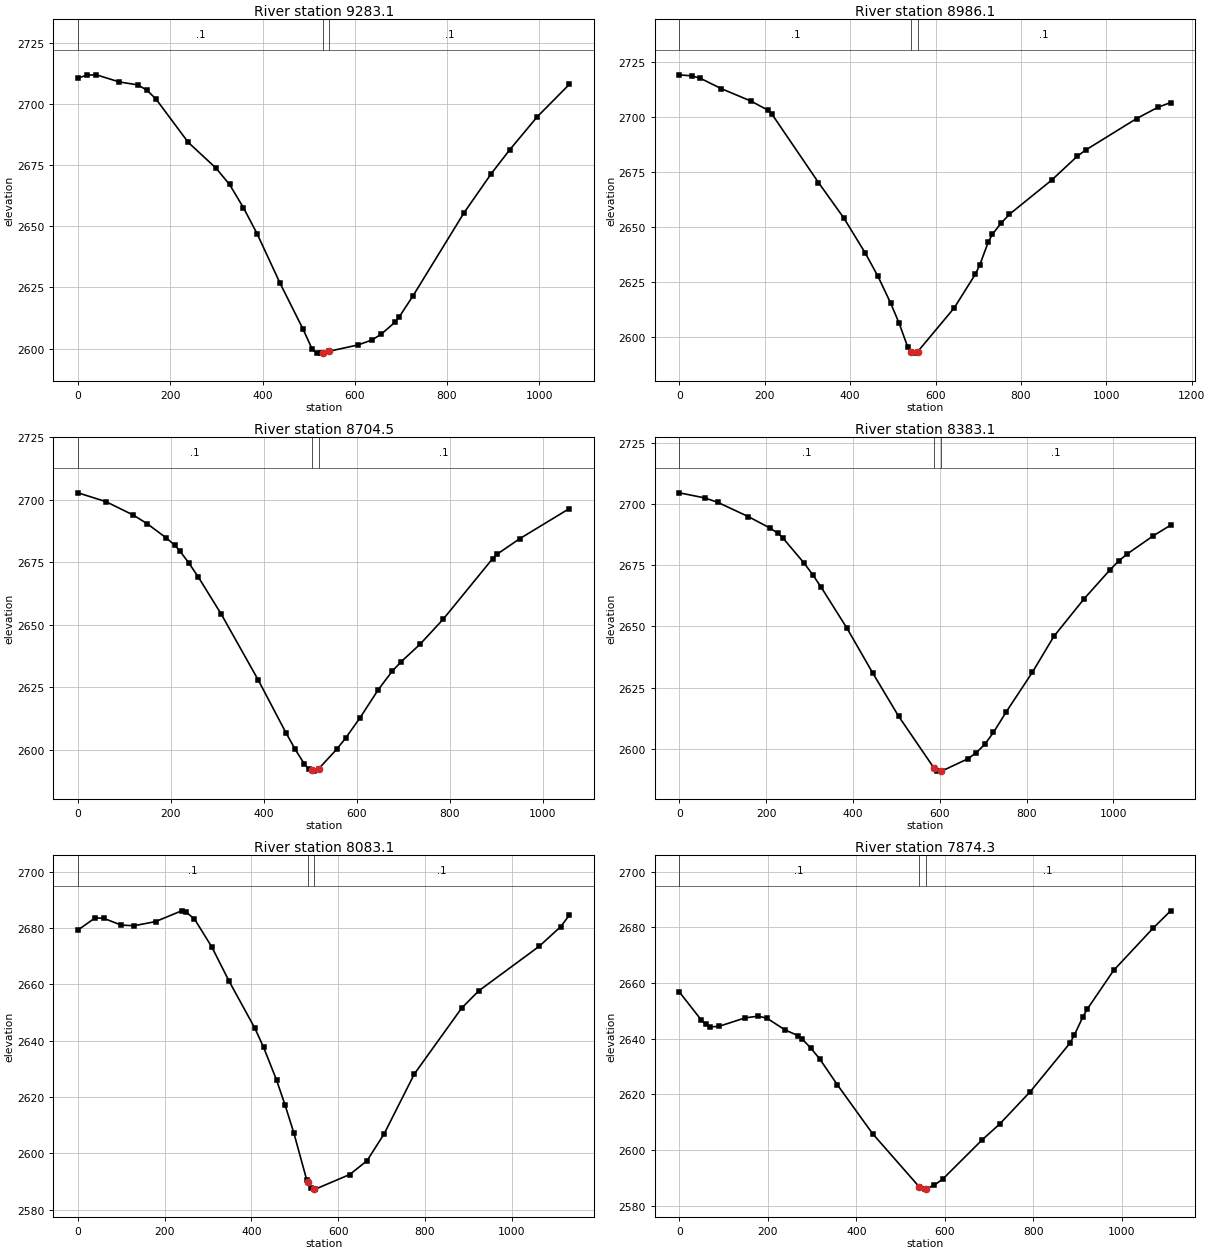
Type RM Length L Ch R = 1 ,9283.1,297.4,297,294.9
XS GIS Cut Line= 3
     1985856.400      339425.267     1985852.575      338887.574
     1985888.033      338361.466
#Sta/Elev= 30
       0 2710.53    19.9 2711.66    39.8 2711.81    89.6 2708.91   129.4 2707.70
   149.4 2705.57   169.3 2701.87   239.0 2684.22   298.7 2673.80   328.6 2667.02
   358.5 2657.60   388.3 2646.90   438.1 2626.68   487.9 2607.92   507.8 2599.71
   517.8 2598.16   527.8 2598.14   530.2 2598.25   545.2 2598.94   607.4 2601.50
   637.2 2603.50   657.1 2605.85   686.9 2610.71   696.9 2613.09   726.7 2621.66
   836.2 2655.27   895.9 2671.45   935.7 2681.14   995.4 2694.64  1065.0 2707.89
#Mann= 3 , 0 , 0
       0     0.1       0   530.2   0.045       0   545.2     0.1       0
Bank Sta=   530.2,   545.2
Exp/Cntr=0.3,0.1

Type RM Length L Ch R = 1 ,8986.1,286.9,281.6,276.2
XS GIS Cut Line= 3
     1986029.741      339461.623     1986137.817      339229.251
     1986117.176      338335.138
#Sta/Elev= 30
       0 2719.20    29.6 2718.71    49.3 2717.61    98.6 2712.88   167.6 2707.25
   207.0 2703.16   216.8 2701.31   325.8 2670.16   385.5 2653.92   435.2 2638.12
   465.0 2627.50   494.8 2615.27   514.6 2606.14   534.5 2595.46   543.2 2592.91
   554.4 2592.46   558.2 2593.14   643.8 2613.06   693.5 2628.48   703.4 2632.49
   723.3 2642.96   733.3 2646.61   753.1 2651.54   773.0 2655.67   872.4 2671.32
   932.0 2682.13   951.9 2684.98  1071.1 2699.30  1120.8 2704.41  1150.6 2706.58
#Mann= 3 , 0 , 0
       0     0.1       0   543.2   0.045       0   558.2     0.1       0
Bank Sta=   543.2,   558.2
Exp/Cntr=0.3,0.1

Type RM Length L Ch R = 1 ,8704.5,311.9,321.3,335.7
XS GIS Cut Line= 3
     1986518.953      339323.997     1986305.775      338568.184
     1986199.624      338318.024
#Sta/Elev= 30
       0 2702.76    59.6 2699.28   119.3 2693.84   149.1 2690.38   188.9 2684.88
   208.8 2681.72   218.7 2679.64   238.6 2674.70   258.4 2669.24   308.2 2654.29
   387.7 2627.99   447.3 2606.91   467.2 2600.27   487.1 2594.35   497.0 2592.24
   502.8 2591.83   507.0 2591.53   517.8 2592.47   556.7 2600.28   576.6 2604.93
   606.4 2612.73   646.1 2624.10   676.0 2631.45   695.8 2635.34   735.6 2642.18
   785.3 2652.15   892.1 2676.46   901.8 2678.25   950.3 2684.41  1057.0 2696.45
#Mann= 3 , 0 , 0
       0     0.1       0   502.8   0.045       0   517.8     0.1       0
Bank Sta=   502.8,   517.8
Exp/Cntr=0.3,0.1

Type RM Length L Ch R = 1 ,8383.1,303.6,299.9,292.6
XS GIS Cut Line= 3
     1986584.987      339407.020     1986681.228      338820.700
     1986879.054      338320.929
#Sta/Elev= 30
       0 2704.49    59.4 2702.38    89.1 2700.56   158.4 2694.82   208.0 2690.20
   227.8 2687.89   237.7 2686.24   287.2 2675.83   307.0 2671.14   326.8 2665.91
   386.2 2649.20   445.6 2630.89   505.0 2613.30   586.7 2592.11   594.2 2590.97
   601.7 2590.89   604.1 2590.87   663.8 2595.83   683.8 2598.34   703.7 2601.86
   723.6 2606.67   753.4 2615.17   813.2 2631.21   862.9 2645.93   932.6 2661.27
   992.3 2673.10  1012.2 2676.69  1032.1 2679.58  1091.8 2686.96  1131.7 2691.27
#Mann= 3 , 0 , 0
       0     0.1       0   586.7   0.045       0   601.7     0.1       0
Bank Sta=   586.7,   601.7
Exp/Cntr=0.3,0.1

Type RM Length L Ch R = 1 ,8083.1,209,208.9,207.3
XS GIS Cut Line= 3
     1986947.112      339480.228     1986947.112      338942.939
     1986981.146      338348.550
#Sta/Elev= 30
       0 2679.25    39.8 2683.59    59.7 2683.38    99.5 2681.00   129.4 2680.77
   179.1 2682.25   238.8 2686.06   248.8 2685.65   268.6 2683.15   308.4 2673.26
   348.2 2661.14   407.9 2644.35   427.8 2637.65   457.7 2626.05   477.6 2617.02
   497.5 2607.30   527.3 2590.56   529.8 2589.82   537.3 2587.58   544.8 2587.36
   547.2 2587.29   626.6 2592.48   666.3 2597.37   706.0 2606.96   775.4 2628.15
   884.6 2651.56   924.3 2657.71  1063.2 2673.46  1112.8 2680.43  1132.6 2684.47
#Mann= 3 , 0 , 0
       0     0.1       0   529.8   0.045       0   544.8     0.1       0
Bank Sta=   529.8,   544.8
Exp/Cntr=0.3,0.1

Type RM Length L Ch R = 1 ,7874.3,390.5,384.6,378.9
XS GIS Cut Line= 3
     1987027.135      339407.976     1987141.261      338955.780
     1987130.494      338311.940
#Sta/Elev= 30
       0 2656.79    49.6 2646.71    59.5 2645.14    69.5 2644.25    89.3 2644.42
   148.8 2647.49   178.6 2648.11   198.5 2647.32   238.2 2643.22   267.9 2641.12
   277.8 2639.85   297.7 2636.54   317.5 2632.67   357.2 2623.44   436.6 2605.93
   541.6 2586.91   555.5 2585.99   556.6 2586.04   575.4 2587.35   595.2 2589.57
   684.3 2603.68   724.0 2609.37   793.3 2621.03   882.4 2638.34   892.4 2641.22
   912.2 2647.91   922.1 2650.68   981.5 2664.54  1070.7 2679.71  1110.3 2685.92
#Mann= 3 , 0 , 0
       0     0.1       0   541.6   0.045       0   556.6     0.1       0
Bank Sta=   541.6,   556.6
Exp/Cntr=0.3,0.1

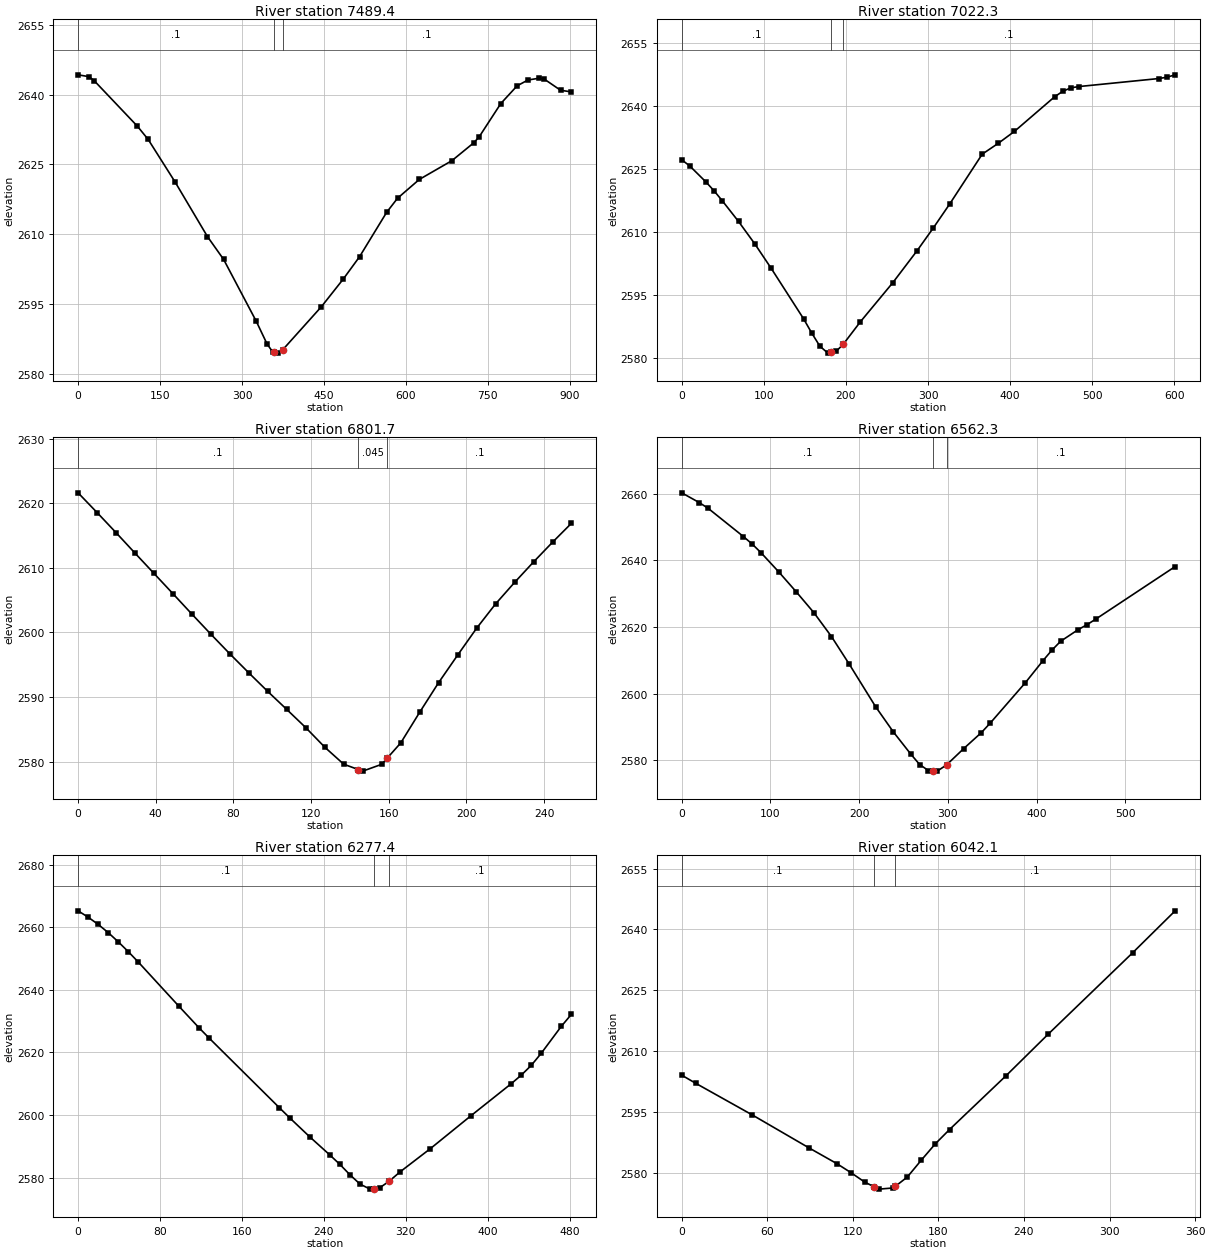
Type RM Length L Ch R = 1 ,7489.4,436.2,467.1,498
XS GIS Cut Line= 3
     1987464.258      339205.565     1987539.952      338950.196
     1987370.870      338336.542
#Sta/Elev= 30
       0 2644.24    19.7 2643.85    29.6 2642.96   108.5 2633.20   128.2 2630.36
   177.6 2621.19   236.8 2609.46   266.4 2604.55   326.0 2591.28   345.9 2586.37
   355.9 2584.72   359.1 2584.62   365.8 2584.42   374.1 2585.09   445.4 2594.42
   485.2 2600.33   515.0 2605.13   564.7 2614.69   584.6 2617.71   624.4 2621.75
   684.1 2625.79   723.8 2629.60   733.8 2630.88   773.6 2638.07   803.4 2641.87
   823.3 2643.13   843.2 2643.50   853.1 2643.32   883.0 2640.92   902.9 2640.57
#Mann= 3 , 0 , 0
       0     0.1       0   359.1   0.045       0   374.1     0.1       0
Bank Sta=   359.1,   374.1
Exp/Cntr=0.3,0.1

Type RM Length L Ch R = 1 ,7022.3,209.7,220.2,230.7
XS GIS Cut Line= 3
     1987720.502      338966.547     1988045.652      338798.588
     1988144.705      338585.410
#Sta/Elev= 30
       0 2627.23     9.9 2625.73    29.7 2621.90    39.6 2619.78    49.5 2617.43
    69.2 2612.52    89.0 2607.18   108.8 2601.40   148.4 2589.33   158.3 2585.94
   168.2 2582.81   178.0 2581.14   181.7 2581.29   187.9 2581.53   196.7 2583.25
   217.6 2588.61   257.2 2597.96   286.8 2605.59   306.6 2611.03   326.4 2616.69
   366.0 2628.57   385.6 2631.16   405.2 2633.99   454.1 2642.23   463.9 2643.53
   473.7 2644.36   483.5 2644.68   581.4 2646.60   591.2 2646.92   601.0 2647.48
#Mann= 3 , 0 , 0
       0     0.1       0   181.7   0.045       0   196.7     0.1       0
Bank Sta=   181.7,   196.7
Exp/Cntr=0.3,0.1

Type RM Length L Ch R = 1 ,6801.7,261.1,239.7,218.3
XS GIS Cut Line= 2
     1987750.649      339095.746     1988004.739      339091.439
#Sta/Elev= 29
       0 2621.62     9.8 2618.56    19.6 2615.44    29.3 2612.29    39.1 2609.14
    48.9 2605.99    58.6 2602.85    68.4 2599.73    78.2 2596.68    88.0 2593.73
    97.7 2590.87   107.5 2588.08   117.3 2585.26   127.1 2582.23   136.8 2579.61
   144.3 2578.79   146.6 2578.54   156.4 2579.60   159.3 2580.58   166.2 2582.92
   175.9 2587.64   185.7 2592.25   195.5 2596.51   205.3 2600.68   215.0 2604.42
   224.8 2607.75   234.6 2610.93   244.4 2613.99   254.1 2616.91
#Mann= 3 , 0 , 0
       0     0.1       0   144.3   0.045       0   159.3     0.1       0
Bank Sta=   144.3,   159.3
Exp/Cntr=0.3,0.1

Type RM Length L Ch R = 1 ,6562.3,302,284.3,266.6
XS GIS Cut Line= 2
     1987778.642      339552.248     1988099.485      339097.899
#Sta/Elev= 30
       0 2660.31    19.9 2657.36    29.8 2655.65    69.5 2647.19    79.5 2644.91
    89.4 2642.32   109.3 2636.59   129.1 2630.58   149.0 2624.32   168.8 2617.16
   188.7 2608.93   218.5 2596.12   238.4 2588.58   258.2 2581.87   268.2 2578.74
   278.1 2576.92   283.5 2576.83   288.0 2576.76   298.5 2578.62   317.8 2583.51
   337.7 2588.31   347.6 2591.13   387.4 2603.32   407.2 2609.92   417.2 2613.05
   427.1 2615.74   447.0 2619.26   456.9 2620.73   466.8 2622.41   556.2 2638.17
#Mann= 3 , 0 , 0
       0     0.1       0   283.5   0.045       0   298.5     0.1       0
Bank Sta=   283.5,   298.5
Exp/Cntr=0.3,0.1

Type RM Length L Ch R = 1 ,6277.4,240.5,235.8,231.2
XS GIS Cut Line= 2
     1988248.064      339586.701     1988159.778      339112.972
#Sta/Elev= 30
       0 2665.30     9.8 2663.27    19.7 2660.94    29.5 2658.31    39.3 2655.37
    49.2 2652.19    59.0 2648.85    98.3 2634.85   118.0 2627.94   127.8 2624.67
   196.7 2602.31   206.5 2599.16   226.2 2593.05   245.9 2587.23   255.7 2584.22
   265.5 2580.91   275.4 2577.91   285.2 2576.31   288.6 2576.49   295.0 2576.83
   303.6 2578.78   314.7 2581.88   344.2 2589.29   383.5 2599.72   422.9 2609.98
   432.7 2612.71   442.6 2615.87   452.4 2619.76   472.0 2628.38   481.9 2632.23
#Mann= 3 , 0 , 0
       0     0.1       0   288.6   0.045       0   303.6     0.1       0
Bank Sta=   288.6,   303.6
Exp/Cntr=0.3,0.1

Type RM Length L Ch R = 1 ,6042.1,222.6,228.5,234.3
XS GIS Cut Line= 2
     1988444.015      339300.849     1988316.701      338979.164
#Sta/Elev= 19
       0 2604.04     9.9 2602.02    49.4 2594.25    89.0 2586.16   108.7 2582.24
   118.6 2580.02   128.5 2577.63   134.7 2576.57   138.4 2575.94   148.3 2576.23
   149.7 2576.61   158.2 2578.93   168.0 2583.09   177.9 2587.14   187.8 2590.64
   227.4 2603.90   257.0 2614.16   316.3 2634.26   346.0 2644.57
#Mann= 3 , 0 , 0
       0     0.1       0   134.7   0.045       0   149.7     0.1       0
Bank Sta=   134.7,   149.7
Exp/Cntr=0.3,0.1

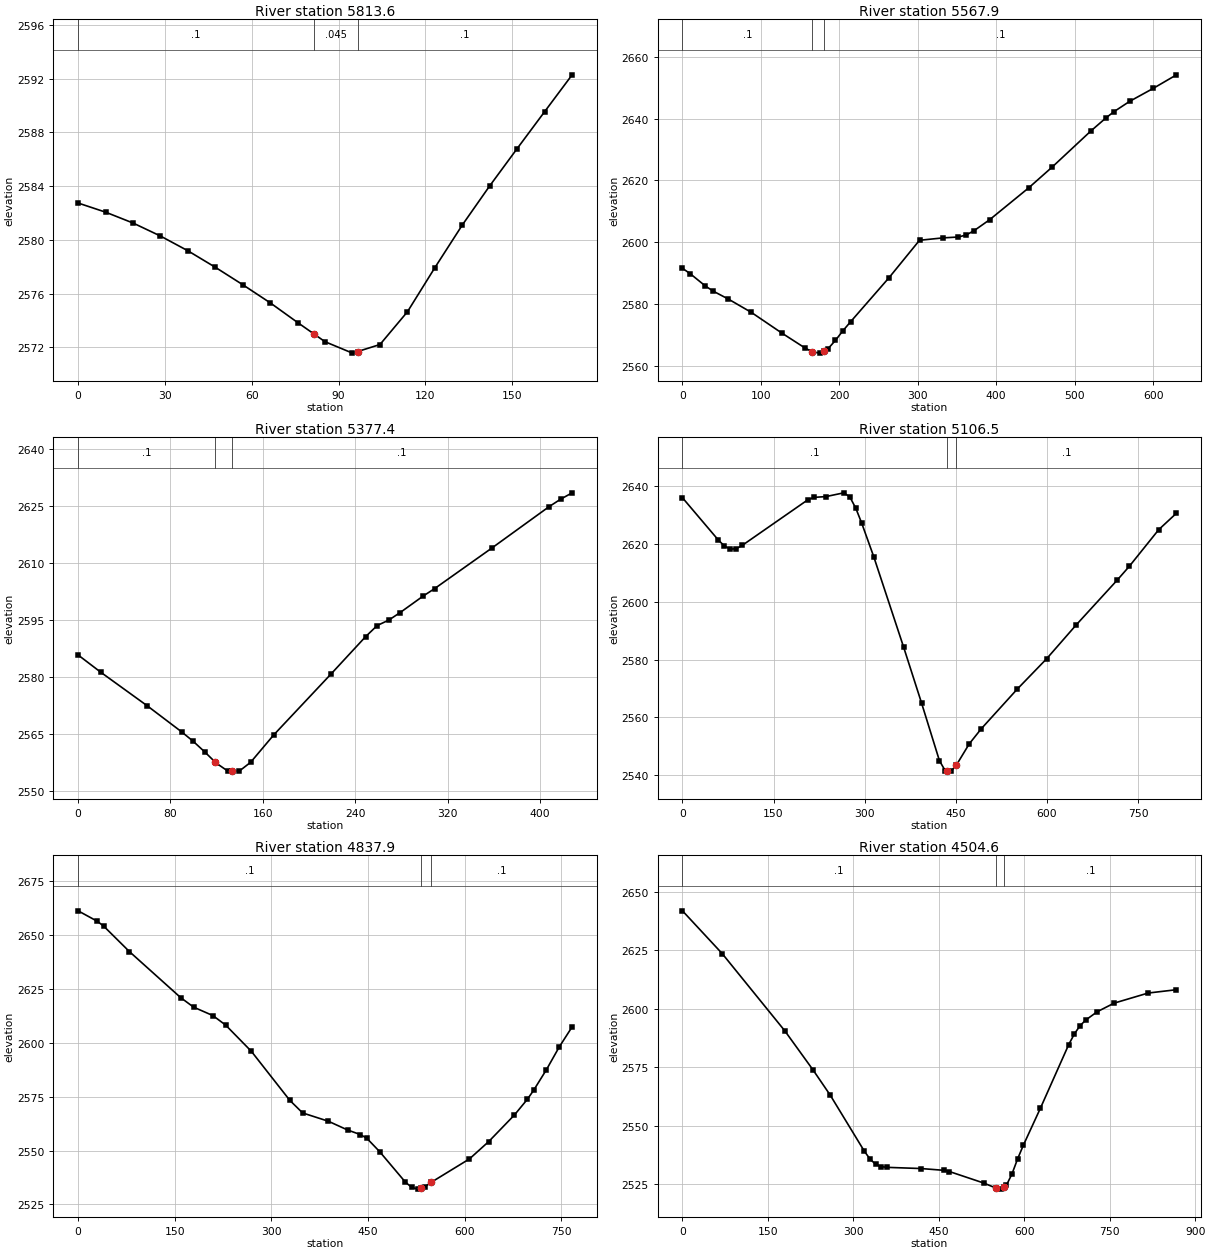
Type RM Length L Ch R = 1 ,5813.6,208.3,245.6,282.9
XS GIS Cut Line= 2
     1988617.088      339184.267     1988597.708      339014.694
#Sta/Elev= 21
       0 2582.74     9.5 2582.06    19.0 2581.25    28.4 2580.29    37.9 2579.19
    47.4 2577.96    56.9 2576.66    66.4 2575.31    75.9 2573.84    81.6 2572.98
    85.3 2572.42    94.8 2571.57    96.6 2571.69   104.3 2572.21   113.8 2574.65
   123.3 2577.94   132.8 2581.12   142.2 2584.01   151.7 2586.79   161.2 2589.54
   170.7 2592.28
#Mann= 3 , 0 , 0
       0     0.1       0    81.6   0.045       0    96.6     0.1       0
Bank Sta=    81.6,    96.6
Exp/Cntr=0.3,0.1

Type RM Length L Ch R = 1 ,5567.9,183.5,190.4,197.4
XS GIS Cut Line= 3
     1988579.674      339250.784     1988881.407      339234.137
     1988997.417      338927.787
#Sta/Elev= 30
       0 2591.54     9.8 2589.81    29.2 2585.82    39.0 2584.18    58.5 2581.59
    87.7 2577.30   126.7 2570.59   156.0 2565.80   165.6 2564.49   175.5 2564.10
   180.6 2564.79   185.2 2565.41   195.0 2568.22   204.7 2571.38   214.5 2574.29
   263.2 2588.46   302.2 2600.61   332.0 2601.38   351.8 2601.67   361.8 2602.33
   371.7 2603.71   391.5 2607.24   441.2 2617.53   471.0 2624.22   520.6 2635.96
   540.4 2640.31   550.4 2642.27   570.2 2645.57   600.0 2649.73   629.8 2654.14
#Mann= 3 , 0 , 0
       0     0.1       0   165.6   0.045       0   180.6     0.1       0
Bank Sta=   165.6,   180.6
Exp/Cntr=0.3,0.1

Type RM Length L Ch R = 1 ,5377.4,305.7,270.9,236.1
XS GIS Cut Line= 3
     1988586.134      339392.903     1988846.685      339459.655
     1988950.044      339339.070
#Sta/Elev= 24
       0 2585.83    19.9 2581.24    59.8 2572.50    89.7 2565.63    99.6 2563.18
   109.6 2560.39   118.4 2557.79   119.5 2557.46   129.5 2555.37   133.4 2555.35
   139.5 2555.33   149.4 2557.65   169.4 2564.84   219.2 2580.90   249.0 2590.66
   259.0 2593.57   269.0 2594.99   278.9 2596.98   298.7 2601.29   308.7 2603.26
   358.3 2613.92   407.9 2624.80   417.9 2626.76   427.8 2628.42
#Mann= 3 , 0 , 0
       0     0.1       0   118.4   0.045       0   133.4     0.1       0
Bank Sta=   118.4,   133.4
Exp/Cntr=0.3,0.1

Type RM Length L Ch R = 1 ,5106.5,275.1,268.6,262.2
XS GIS Cut Line= 3
     1988650.733      340079.810     1988809.283      339552.084
     1988972.452      339346.668
#Sta/Elev= 30
       0 2635.87    59.0 2621.28    68.9 2619.24    78.7 2618.13    88.6 2618.27
    98.4 2619.42   206.6 2635.19   216.5 2636.00   236.2 2636.27   265.7 2637.57
   275.5 2636.17   285.4 2632.26   295.2 2627.06   314.9 2615.55   364.1 2584.32
   393.6 2565.04   423.1 2545.09   433.0 2541.47   436.2 2541.51   442.8 2541.58
   451.2 2543.62   472.3 2550.92   492.0 2556.10   551.0 2569.74   599.6 2580.27
   648.2 2591.94   716.2 2607.52   735.6 2612.16   784.2 2624.86   813.4 2630.54
#Mann= 3 , 0 , 0
       0     0.1       0   436.2   0.045       0   451.2     0.1       0
Bank Sta=   436.2,   451.2
Exp/Cntr=0.3,0.1

Type RM Length L Ch R = 1 ,4837.9,323.4,333.3,343.1
XS GIS Cut Line= 2
     1989040.733      340185.303     1989044.790      339418.743
#Sta/Elev= 30
       0 2661.17    29.9 2656.30    39.8 2654.04    79.6 2642.26   159.3 2620.88
   179.2 2616.50   209.1 2612.59   229.0 2608.16   268.8 2596.02   328.5 2573.27
   348.4 2567.43   388.3 2563.58   418.1 2559.53   438.0 2557.39   448.0 2555.68
   467.9 2549.48   507.7 2535.39   517.7 2532.87   527.6 2532.09   532.7 2532.57
   537.6 2533.03   547.7 2535.21   607.3 2546.11   637.2 2554.16   677.0 2566.46
   696.9 2573.67   706.8 2577.90   726.8 2587.53   746.7 2598.09   766.6 2607.35
#Mann= 3 , 0 , 0
       0     0.1       0   532.7   0.045       0   547.7     0.1       0
Bank Sta=   532.7,   547.7
Exp/Cntr=0.3,0.1

Type RM Length L Ch R = 1 ,4504.6,424.3,434.5,444.6
XS GIS Cut Line= 3
     1989138.385      340120.942     1989411.687      339533.106
     1989434.539      339315.384
#Sta/Elev= 30
       0 2641.97    69.8 2623.65   179.5 2590.66   229.4 2573.81   259.3 2563.12
   319.1 2539.17   329.1 2535.77   339.1 2533.46   349.1 2532.49   359.0 2532.18
   418.9 2531.67   458.8 2530.91   468.7 2530.38   528.6 2525.49   549.7 2523.38
   558.5 2522.86   564.7 2523.83   568.5 2524.43   578.4 2529.34   588.4 2535.85
   598.4 2541.64   628.3 2557.47   678.1 2584.75   688.1 2589.34   698.0 2592.83
   708.0 2595.24   727.9 2598.76   757.7 2602.46   817.4 2606.78   867.2 2608.21
#Mann= 3 , 0 , 0
       0     0.1       0   549.7   0.045       0   564.7     0.1       0
Bank Sta=   549.7,   564.7
Exp/Cntr=0.3,0.1

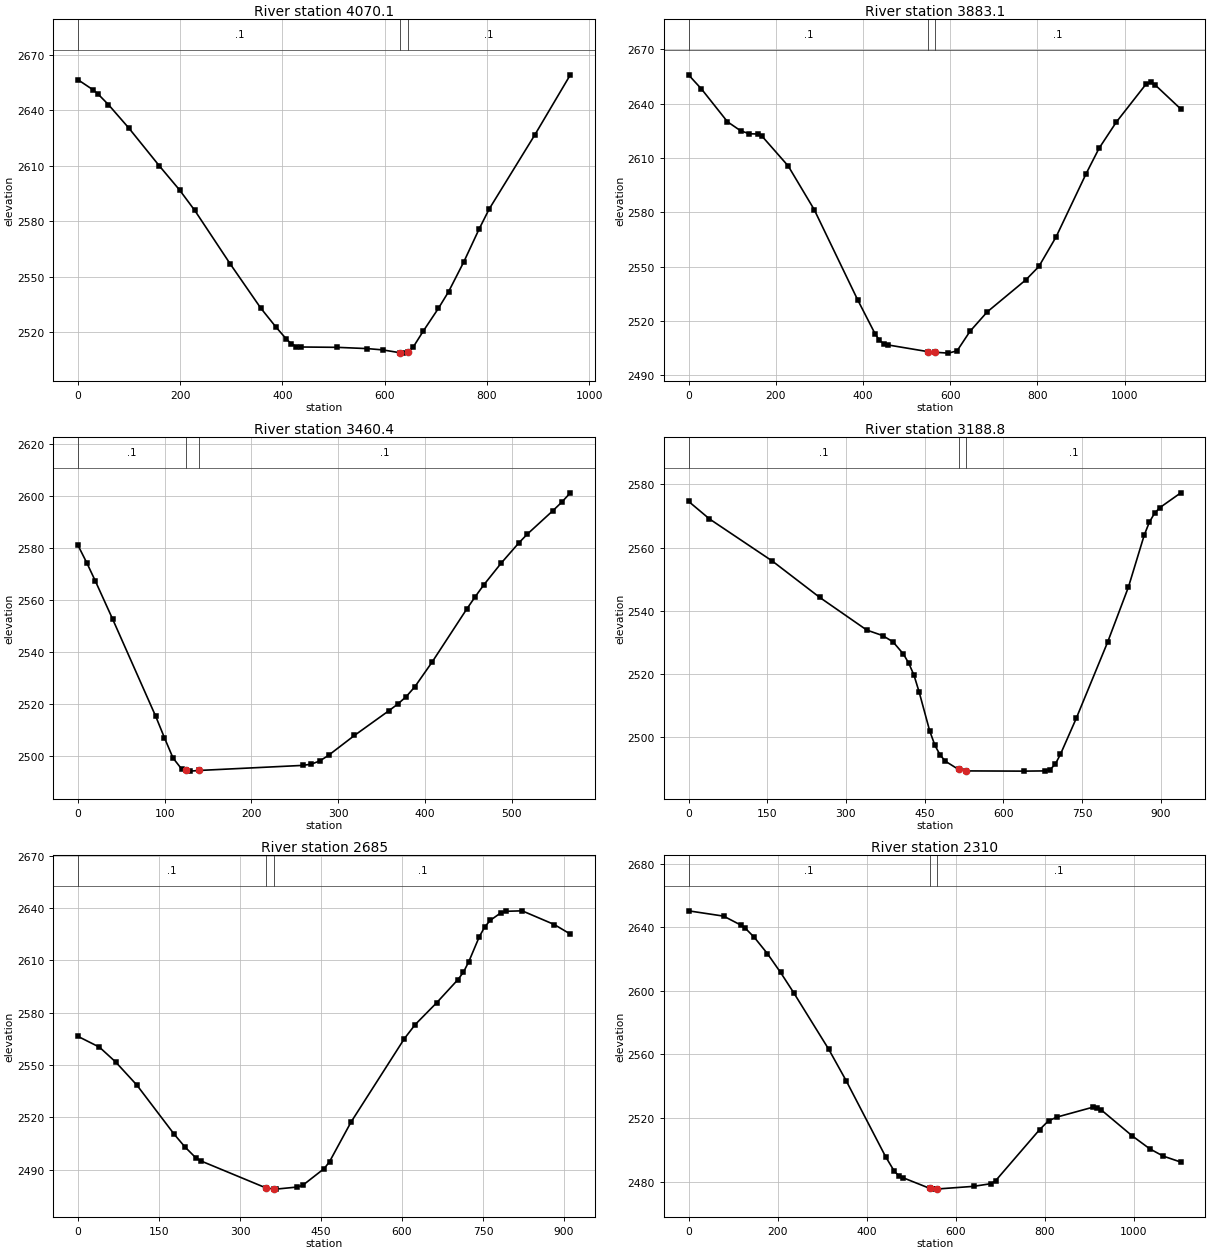
Type RM Length L Ch R = 1 ,4070.1,183.5,187,194.4
XS GIS Cut Line= 2
     1989190.995      340248.345     1989953.488      339659.914
#Sta/Elev= 30
       0 2656.60    29.8 2651.09    39.7 2648.72    59.6 2643.10    99.3 2630.47
   158.9 2610.01   198.6 2596.90   228.4 2585.80   297.9 2556.75   357.5 2532.88
   387.2 2522.61   407.1 2516.27   417.0 2513.60   427.0 2512.08   436.9 2511.81
   506.4 2511.63   566.0 2510.94   595.8 2510.25   630.8 2508.66   635.5 2508.49
   645.8 2509.20   655.3 2511.58   675.2 2520.35   705.0 2532.74   724.8 2541.72
   754.6 2557.88   784.4 2575.59   804.3 2586.55   893.6 2626.74   963.1 2659.29
#Mann= 3 , 0 , 0
       0     0.1       0   630.8   0.045       0   645.8     0.1       0
Bank Sta=   630.8,   645.8
Exp/Cntr=0.3,0.1

Type RM Length L Ch R = 1 ,3883.1,435.3,422.4,405.6
XS GIS Cut Line= 3
     1989225.618      340316.935     1989710.566      340043.777
     1990246.461      339843.675
#Sta/Elev= 30
       0 2655.92    29.8 2648.08    89.4 2629.99   119.3 2625.06   139.2 2623.37
   159.0 2623.24   169.0 2621.91   228.6 2605.57   288.2 2581.48   387.6 2531.76
   427.4 2513.06   437.3 2509.42   447.3 2507.40   457.2 2506.75   549.1 2503.04
   564.1 2502.72   596.0 2502.23   615.8 2503.52   645.4 2514.29   684.8 2524.99
   773.6 2542.74   803.2 2550.07   842.6 2566.37   911.6 2601.35   941.2 2615.35
   980.7 2629.79  1049.7 2651.03  1059.6 2651.70  1069.4 2650.43  1128.6 2637.03
#Mann= 3 , 0 , 0
       0     0.1       0   549.1   0.045       0   564.1     0.1       0
Bank Sta=   549.1,   564.1
Exp/Cntr=0.3,0.1

Type RM Length L Ch R = 1 ,3460.4,274,271.5,269
XS GIS Cut Line= 2
     1989875.969      340486.786     1990149.439      339989.371
#Sta/Elev= 30
       0 2580.84    10.0 2574.22    19.9 2567.21    39.8 2552.61    89.6 2515.16
    99.6 2506.97   109.5 2499.18   119.5 2494.92   124.8 2494.50   129.5 2494.13
   139.8 2494.39   258.9 2496.33   268.9 2496.80   278.8 2498.06   288.8 2500.20
   318.7 2507.84   358.5 2517.36   368.5 2519.86   378.4 2522.76   388.4 2526.57
   408.3 2536.06   448.1 2556.37   458.1 2561.22   468.0 2565.76   488.0 2574.09
   507.9 2581.68   517.8 2585.12   547.7 2594.25   557.7 2597.45   567.6 2601.05
#Mann= 3 , 0 , 0
       0     0.1       0   124.8   0.045       0   139.8     0.1       0
Bank Sta=   124.8,   139.8
Exp/Cntr=0.3,0.1

Type RM Length L Ch R = 1 ,3188.8,484.8,503.8,522.9
XS GIS Cut Line= 3
     1989951.795      340971.212     1990136.519      340594.452
     1990336.778      340116.416
#Sta/Elev= 30
       0 2574.66    40.0 2569.07   159.8 2555.71   249.8 2544.23   339.7 2533.85
   369.7 2532.12   389.6 2530.13   409.6 2526.22   419.6 2523.36   429.6 2519.54
   439.5 2514.17   459.5 2501.91   469.4 2497.35   479.4 2494.25   489.4 2492.29
   514.6 2489.67   529.6 2489.22   638.9 2489.15   678.8 2489.22   688.7 2489.62
   698.7 2491.33   708.6 2494.48   738.6 2505.83   798.4 2529.99   838.2 2547.52
   868.1 2563.88   878.1 2568.10   888.1 2570.92   898.0 2572.66   937.9 2577.35
#Mann= 3 , 0 , 0
       0     0.1       0   514.6   0.045       0   529.6     0.1       0
Bank Sta=   514.6,   529.6
Exp/Cntr=0.3,0.1

Type RM Length L Ch R = 1 ,2685,373.2,374.9,375.8
XS GIS Cut Line= 2
     1990196.812      340874.382     1991054.943      340566.088
#Sta/Elev= 30
       0 2566.35    39.6 2560.20    69.4 2551.78   109.0 2538.44   178.4 2510.17
   198.2 2502.95   218.0 2496.83   228.0 2494.94   348.3 2479.51   363.3 2478.85
   366.7 2478.84   406.4 2480.05   416.3 2481.06   455.9 2490.61   465.8 2494.56
   505.5 2517.20   604.6 2565.15   624.4 2573.11   664.0 2585.56   703.7 2598.93
   713.6 2603.05   723.5 2609.01   743.3 2623.54   753.2 2629.02   763.2 2632.80
   783.0 2637.14   792.9 2638.04   822.6 2638.31   882.1 2630.45   911.8 2624.98
#Mann= 3 , 0 , 0
       0     0.1       0   348.3   0.045       0   363.3     0.1       0
Bank Sta=   348.3,   363.3
Exp/Cntr=0.3,0.1

Type RM Length L Ch R = 1 ,2310,474,474.2,475.1
XS GIS Cut Line= 3
     1990117.747      341248.561     1990658.511      341098.572
     1991172.969      340919.320
#Sta/Elev= 30
       0 2650.33    78.8 2647.00   118.1 2641.29   128.0 2639.26   147.7 2633.68
   177.2 2623.44   206.8 2611.57   236.3 2598.81   315.0 2563.22   354.4 2543.33
   443.0 2495.53   462.7 2486.31   472.6 2483.68   482.4 2482.32   542.2 2475.66
   551.3 2475.20   557.2 2475.25   640.4 2476.95   680.0 2478.65   690.0 2480.51
   789.0 2512.70   808.8 2518.19   828.6 2520.61   907.9 2526.71   917.8 2526.39
   927.7 2524.94   997.0 2508.67  1036.6 2500.51  1066.4 2495.99  1106.0 2492.22
#Mann= 3 , 0 , 0
       0     0.1       0   542.2   0.045       0   557.2     0.1       0
Bank Sta=   542.2,   557.2
Exp/Cntr=0.3,0.1

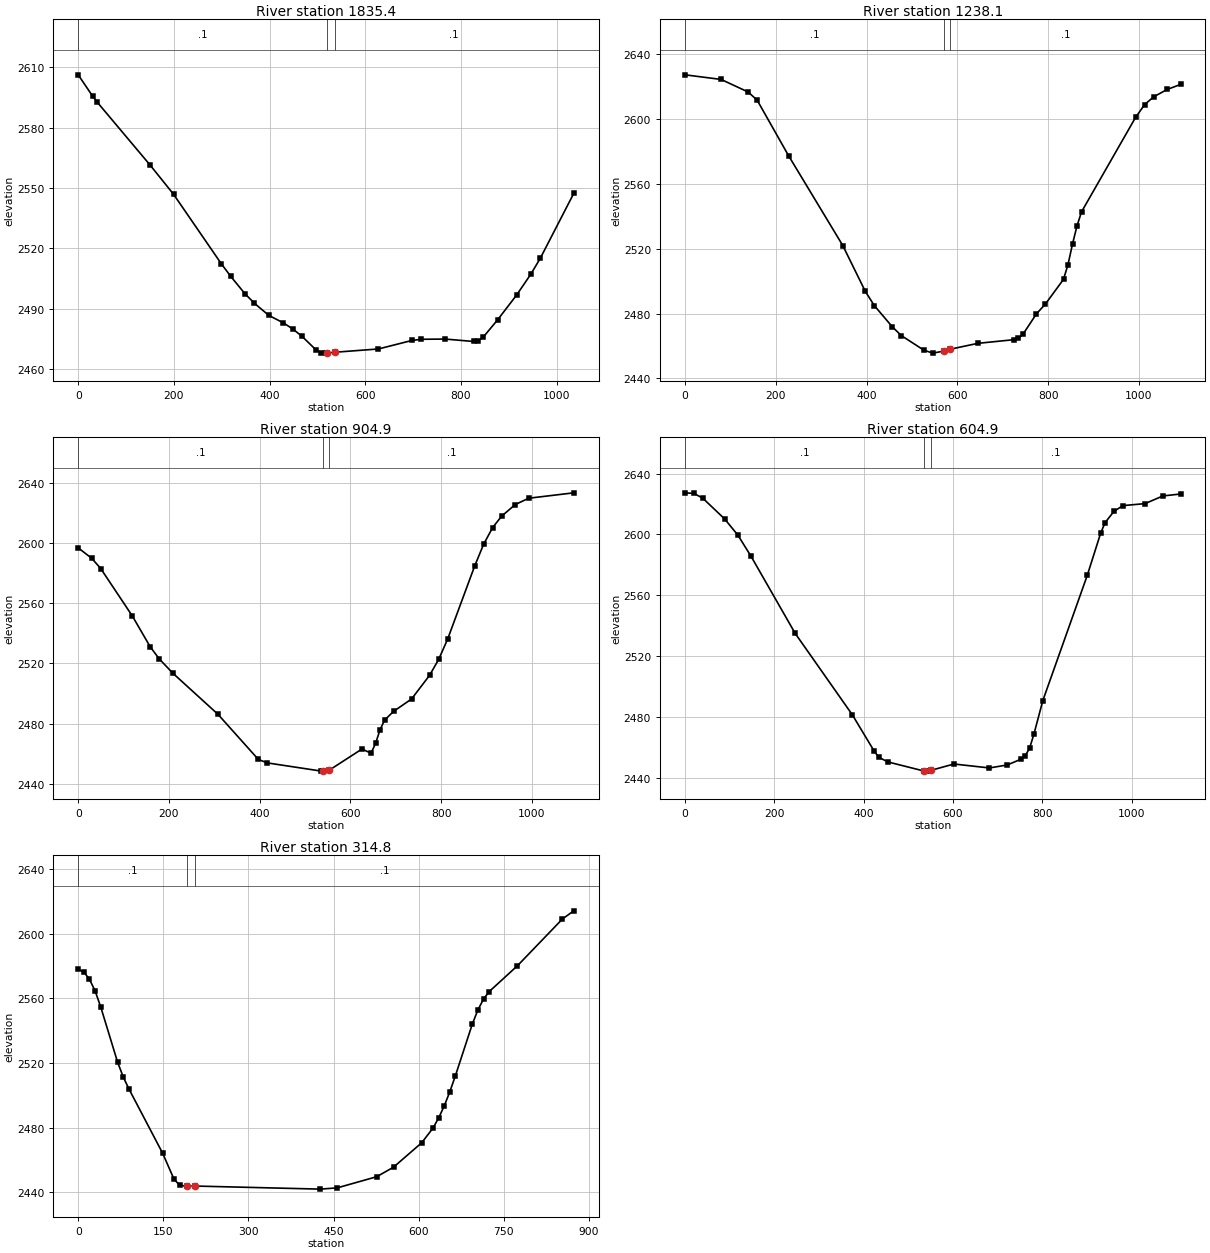
Type RM Length L Ch R = 1 ,1835.4,612.5,597.5,582.6
XS GIS Cut Line= 2
     1990272.178      341638.808     1991275.622      341382.564
#Sta/Elev= 30
       0 2606.25    29.9 2595.75    39.8 2592.65   149.4 2561.67   199.2 2546.94
   298.7 2512.52   318.7 2506.14   348.5 2497.50   368.4 2492.74   398.3 2486.75
   428.2 2483.09   448.1 2480.07   468.0 2476.28   497.9 2469.39   507.9 2468.16
   517.8 2468.00   520.9 2468.07   535.9 2468.43   627.4 2470.07   697.1 2474.28
   717.0 2474.88   766.8 2474.99   826.5 2473.78   836.5 2474.19   846.4 2475.94
   876.3 2484.49   916.2 2496.86   946.0 2507.27   965.9 2515.23  1035.6 2547.36
#Mann= 3 , 0 , 0
       0     0.1       0   520.9   0.045       0   535.9     0.1       0
Bank Sta=   520.9,   535.9
Exp/Cntr=0.3,0.1

Type RM Length L Ch R = 1 ,1238.1,326.6,333.2,339.8
XS GIS Cut Line= 3
     1990883.572      342290.624     1991214.898      341856.639
     1991547.800      341423.867
#Sta/Elev= 30
       0 2627.18    79.4 2624.34   139.0 2616.59   158.8 2611.58   228.3 2577.22
   347.5 2521.97   397.1 2493.73   417.0 2484.94   456.7 2471.83   476.5 2466.45
   526.2 2457.45   546.0 2455.63   569.5 2456.86   584.5 2458.06   645.3 2461.67
   724.7 2463.92   734.6 2464.72   744.6 2467.26   774.3 2479.86   794.2 2485.96
   833.9 2501.12   843.8 2510.20   853.8 2522.97   863.7 2534.13   873.6 2542.72
   992.7 2600.93  1012.6 2608.79  1032.4 2613.59  1062.2 2618.14  1092.0 2621.28
#Mann= 3 , 0 , 0
       0     0.1       0   569.5   0.045       0   584.5     0.1       0
Bank Sta=   569.5,   584.5
Exp/Cntr=0.3,0.1

Type RM Length L Ch R = 1 ,904.9,299.5,300,295.4
XS GIS Cut Line= 3
     1991024.195      342384.002     1991467.841      342065.734
     1991911.487      341747.467
#Sta/Elev= 30
       0 2597.01    29.8 2590.08    49.6 2583.26   119.1 2551.72   158.8 2531.04
   178.7 2523.01   208.5 2513.53   307.8 2486.18   397.1 2456.02   417.0 2453.74
   536.1 2448.27   538.5 2448.28   553.5 2448.97   625.4 2463.01   645.3 2460.18
   655.2 2466.71   665.1 2475.75   675.0 2482.20   694.9 2488.06   734.6 2496.34
   774.3 2512.10   794.2 2522.64   814.0 2536.16   873.6 2584.87   893.4 2599.43
   913.3 2610.57   933.2 2618.17   963.0 2625.85   992.7 2630.08  1092.0 2633.68
#Mann= 3 , 0 , 0
       0     0.1       0   538.5   0.045       0   553.5     0.1       0
Bank Sta=   538.5,   553.5
Exp/Cntr=0.3,0.1

Type RM Length L Ch R = 1 ,604.9,301.8,290,283.2
XS GIS Cut Line= 3
     1991184.535      342622.461     1991632.220      342316.544
     1992019.043      341901.443
#Sta/Elev= 30
       0 2627.30    19.7 2626.91    39.4 2623.85    88.7 2610.09   118.3 2599.46
   147.9 2585.47   246.5 2534.90   374.6 2481.31   423.9 2457.25   433.8 2453.46
   453.5 2450.40   534.7 2444.39   542.2 2444.31   549.7 2444.76   602.0 2448.99
   681.6 2446.40   721.4 2448.36   751.3 2452.05   761.2 2454.27   771.2 2459.22
   781.1 2468.63   801.0 2490.66   900.6 2573.07   930.4 2600.67   940.4 2607.70
   960.3 2615.11   980.2 2618.89  1030.0 2620.21  1069.8 2625.25  1109.6 2626.53
#Mann= 3 , 0 , 0
       0     0.1       0   534.7   0.045       0   549.7     0.1       0
Bank Sta=   534.7,   549.7
Exp/Cntr=0.3,0.1

Type RM Length L Ch R = 1 ,314.8,311.1,314.7,318.4
XS GIS Cut Line= 2
     1991686.905      342743.458     1992071.382      341959.714
#Sta/Elev= 30
       0 2578.03     9.9 2576.29    19.8 2571.82    29.8 2564.59    39.7 2554.68
    69.4 2520.54    79.4 2511.31    89.3 2504.01   148.8 2464.18   168.6 2448.29
   178.6 2444.41   190.8 2443.87   205.8 2443.91   426.6 2442.00   456.3 2442.78
   525.8 2449.67   555.5 2455.58   605.1 2470.67   625.0 2479.76   634.9 2485.95
   644.8 2493.44   654.7 2502.27   664.6 2512.24   694.4 2544.21   704.3 2552.99
   714.2 2559.67   724.2 2564.24   773.8 2580.17   853.1 2609.11   873.0 2614.14
#Mann= 3 , 0 , 0
       0     0.1       0   190.8   0.045       0   205.8     0.1       0
Bank Sta=   190.8,   205.8
Exp/Cntr=0.3,0.1